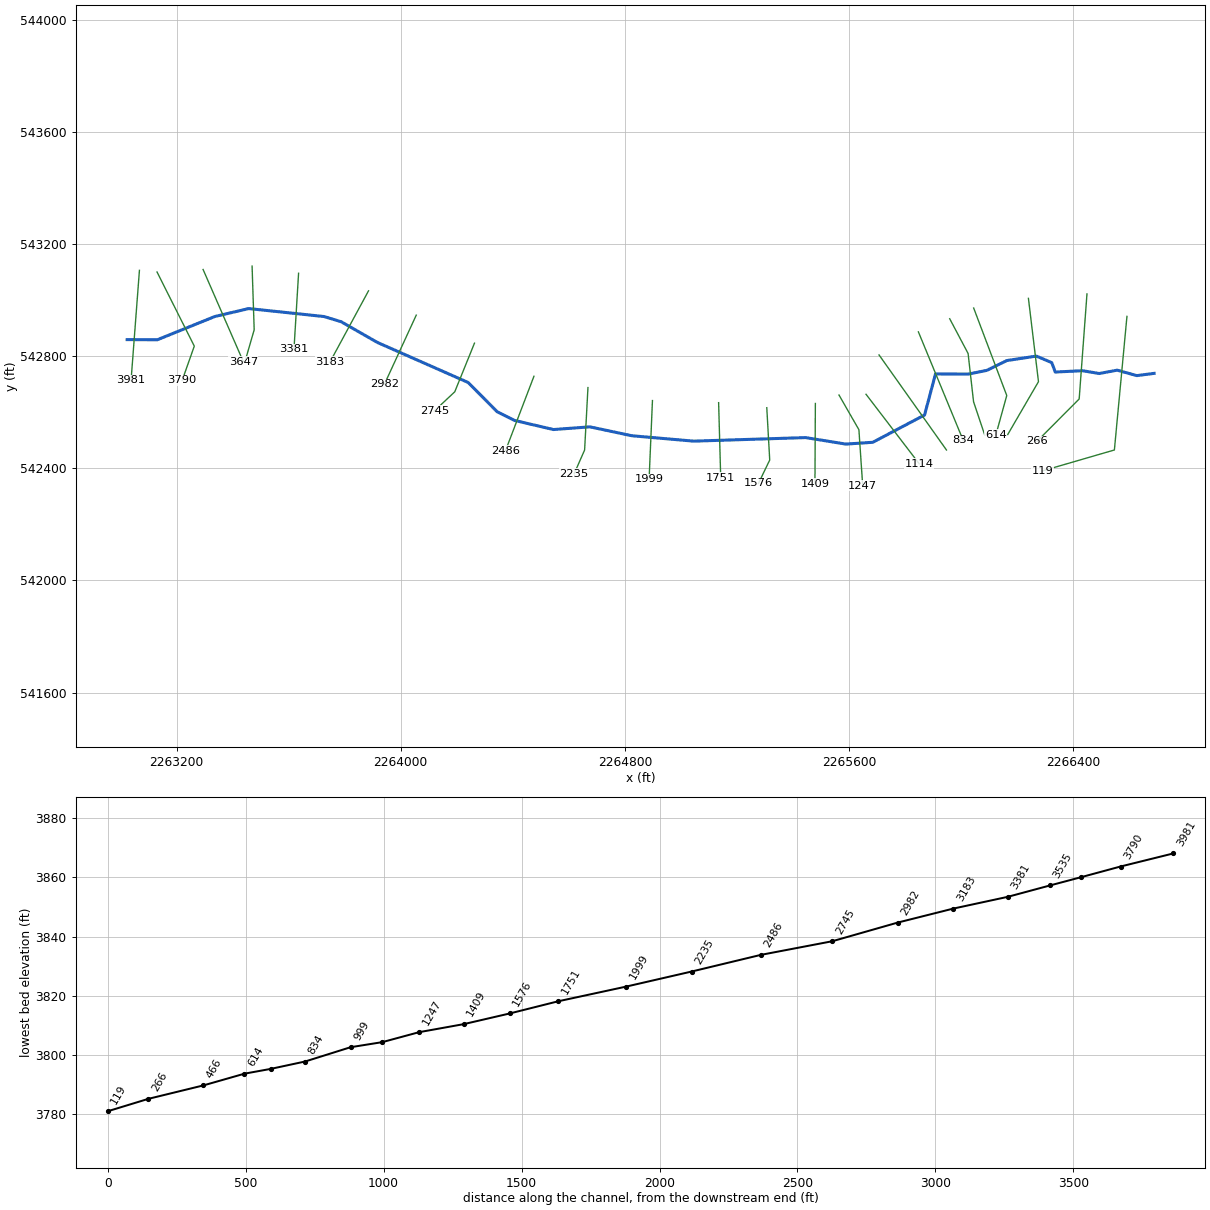
--- RCKYRN.prj (project) ---

Proj Title=RCKYRN
Current Plan=p01
Default Exp/Contr=0,0
English Units
Geom File=g01
Flow File=f01
Plan File=p01
Background Map Layer=Inundation Boundary (01pct Value_0)
BEGIN DESCRIPTION:
Stream Name: Rocky Run
Flood Zone: Approximate
Pocahontas County, WV
HEC-RAS Version: RAS 6.1.0
Vertical Datum: NAVD88
Projection: NAD 1983 StatePlane West Virginia S FIPS 4702 (US Feet)
Terrain: 1-meter LIDAR (FEMA Region III 3DEP collected 2016-2018)
Land Use: 2019 NLCD
Hydrologic Method:
WV SIR2010-5033 regression equations
END DESCRIPTION:
DSS File=dss
DSS Export Rating Curves= 0
DSS Export Rating Curve Sorted= 0
DSS Export Volume Flow Curves= 0
DXF OffsetX= 0
DXF OffsetY= 0
DXF ScaleX= 0
DXF ScaleY= 0

--- RCKYRN.p01 (plan) ---

Plan Title=Floodplain
Program Version=6.10
Short Identifier=Floodplain
Geom File=g01
Flow File=f01
Subcritical Flow
K Sum by GR= 0
Std Step Tol= 0.01
Critical Tol= 0.01
Num of Std Step Trials= 20
Max Error Tol= 0.3
Flow Tol Ratio= 0.001
Split Flow NTrial= 30
Split Flow Tol= 0.02
Split Flow Ratio= 0.02
Log Output Level= 0
Friction Slope Method= 1
Unsteady Friction Slope Method= 2
Unsteady Bridges Friction Slope Method= 1
Parabolic Critical Depth
Global Vel Dist= 0 , 0 , 0
Global Log Level= 0
CheckData=True
Encroach Param=-1 ,0,0, 0
Computation Interval=0.1SEC
Output Interval=1SEC
Instantaneous Interval=Max Profile
Mapping Interval=1HOUR
Computation Time Step Use Courant=        0
Computation Time Step Use Time Series=    0
Computation Time Step Count To Double=0
Computation Time Step Max Doubling=0
Computation Time Step Max Halving=0
Computation Time Step Residence Courant=0
Run HTab= 0
Run UNet= 0
Run Sediment= 0
Run PostProcess= 0
Run WQNet= 0
Run RASMapper=-1
UNET Theta= 0
UNET Theta Warmup= 0
UNET ZTol= 0
UNET ZSATol= 0
UNET MxIter= 0
UNET Max Iter WO Improvement= 0
UNET MaxInSteps= 0
UNET DtIC= 0
UNET DtMin= 0
UNET MaxCRTS= 0
UNET WFStab= 0
UNET SFStab= 0
UNET WFX= 1
UNET SFX= 1
UNET Gravity=32.174
UNET 1D Methodology=Finite Difference
UNET DSS MLevel= 1
UNET Pardiso=0
UNET DZMax Abort= 0
UNET Use Existing IB Tables= 0
UNET Froude Reduction=False
UNET Froude Limit= 0
UNET Froude Power= 0
UNET D1 Cores= 0
UNET WindReference=Eulerian
UNET WindDragFormulation=Hsu (1988)
UNET D2 Coriolis=0
UNET D2 Cores= 0
UNET D2 Theta= 1
UNET D2 Theta Warmup= 1
UNET D2 Z Tol= 0.01
UNET D2 Volume Tol= 0.01
UNET D2 Max Iterations= 20
UNET D2 Equation= 0
UNET D2 RampUpFraction=0.1
UNET D2 TimeSlices= 1
UNET D2 Turbulence Formulation=Non-Conservative (original)
UNET D2 Eddy Viscosity=0.3
UNET D2 Transverse Eddy Viscosity=0.1
UNET D2 Smagorinsky Mixing=0
UNET D2 BCVolumeCheck=0
UNET D2 Cores=0
UNET D2 SolverType=PARDISO (Direct)
UNET D2 Minimum Iterations= 2147483647
UNET D2 Maximum Iterations= 2147483647
UNET D2 Restart Number= 10
UNET D2 Relaxation Coeff=1.3
UNET D2 SOR Precondition Iterations= 10
UNET D2 ILUT Maximum Fill= 8
UNET D2 ILUT Tolerance=1E-08
UNET D1D2 MaxIter= 0
UNET D1D2 ZTol=0.01
UNET D1D2 QTol=0.1
UNET D1D2 MinQTol=1
DSS File=dss
Write IC File= 0
Write IC File at Fixed DateTime=0
Write IC File at Sim End=0
Echo Input=False
Echo Parameters=False
Echo Output=False
Write Detailed= 0
HDF Write Warmup=0
HDF Write Time Slices=0
HDF Flush=0
HDF Compression= 1
HDF Chunk Size= 1
HDF Spatial Parts= 1
HDF Use Max Rows=0
HDF Fixed Rows= 1
Calibration Method= 0
Calibration Iterations= 20
Calibration Max Change=0.05
Calibration Tolerance=0.2
Calibration Maximum=1.5
Calibration Minimum=0.5
Calibration Optimization Method= 1
WQ AD Non Conservative
WQ ULTIMATE=-1
WQ Max Comp Step=1HOUR
WQ Output Interval=15MIN
WQ Output Selected Increments= 0
WQ Output face flow=0
WQ Output face velocity=0
WQ Output face area=0
WQ Output face dispersion=0
WQ Output cell volume=0
WQ Output cell surface area=0
WQ Output cell continuity=0
WQ Output cumulative cell continuity=0
WQ Output face conc=0
WQ Output face dconc_dx=0
WQ Output face courant=0
WQ Output face peclet=0
WQ Output face adv mass=0
WQ Output face disp mass=0
WQ Output cell mass=0
WQ Output cell source sink temp=0
WQ Output nsm pathways=0
WQ Output nsm derived pathways=0
WQ Create Restart=0
WQ Fixed Restart=0
WQ System Summary=0
WQ Write To DSS=0
Sorting and Armoring Iterations= 10
XS Update Threshold= 0.02
Bed Roughness Predictor= 0
Hydraulics Update Threshold= 0.02
Energy Slope Method= 1
Volume Change Method= 1
Sediment Retention Method= 0
Sediment TS Multiplier= 1
Warm Up Method= 0
XS Weighting Method= 0
Number of US Weighted Cross Sections= 1
Number of DS Weighted Cross Sections= 1
Upstream XS Weight=0
Main XS Weight=1
Downstream XS Weight=0
Number of DS XS's Weighted with US Boundary= 1
Upstream Boundary Weight= 1
Weight of XSs Associated with US Boundary= 0
Number of US XS's Weighted with DS Boundary= 1
Downstream Boundary Weight= 0.5
Weight of XSs Associated with DS Boundary= 0.5
Percentile Method= 0
Sediment Output Level= 3
Mass or Volume Output= 0
Output Increment Type= 1
Profile and TS Output Increment= 1
Transport Output Increment 1
XS Output Flag= 0
XS Output Increment= 10
Read HDF5 Sediment Hotstart= 0
Sediment Hotstart Type= 0
Write Gradation File= 0
Read Gradation Hotstart= 0
Write HDF5 File= 1
Write Binary Output= 1
Write DSS Sediment File= 0
DSS Sediment Output Type= 1
SV Curve= 0
Specific Gage Flag= 0
Subcell Erosion Methods= 0
Subcell Deposition Methods= 0
Advection Scheme= 1
Matrix Solver= 0
Implicit Weighting Factor= 1
Maximum Outer Loop Convergence Iterations= 5
Convergence Maximum Absolute= 0.001
Convergence RMSE= 0.0001
Grain Fractions Max Abs Error= 0.001
Max Subgrid Regions= 1
Max Subgrid Length Scale= 3.402823E+38
Initial Layer Thickness= 3.402823E+38
Min Layer Thickness= 3.402823E+38
Max Layer Thickness= 3.402823E+38
Number of Layers= 5

--- RCKYRN.f01 (steady flow) ---

Flow Title=Flow
Program Version=6.10
Number of Profiles= 6
Profile Names=01pct,10pct,04pct,02pct,0_2pct,01plus
River Rch & RM=RCKYRN,Main            ,3981
     643     341     453     545     896     951
Boundary for River Rch & Prof#=RCKYRN,Main            , 1
Up Type= 0
Dn Type= 3
Dn Slope=0.02687
Boundary for River Rch & Prof#=RCKYRN,Main            , 2
Up Type= 0
Dn Type= 3
Dn Slope=0.02687
Boundary for River Rch & Prof#=RCKYRN,Main            , 3
Up Type= 0
Dn Type= 3
Dn Slope=0.02687
Boundary for River Rch & Prof#=RCKYRN,Main            , 4
Up Type= 0
Dn Type= 3
Dn Slope=0.02687
Boundary for River Rch & Prof#=RCKYRN,Main            , 5
Up Type= 0
Dn Type= 3
Dn Slope=0.02687
Boundary for River Rch & Prof#=RCKYRN,Main            , 6
Up Type= 0
Dn Type= 3
Dn Slope=0.02687
DSS Import GetInterval= 0
DSS Import GetPeak= 0
DSS Import FillOption= 0

--- RCKYRN.g01 (geometry) ---

Geom Title=Geometry
Program Version=6.10

River Reach=RCKYRN          ,Main
Reach XY= 30
     2263023.501      542859.693     2263131.342      542859.175
     2263336.436      542942.092     2263457.466      542970.487
      2263726.61      542942.001     2263787.623      542923.435
     2263916.699      542849.557     2264240.556       542706.72
     2264344.873       542601.79     2264406.366      542571.175
     2264545.304      542538.645     2264675.257      542548.298
     2264825.294      542516.4752265045.78401279542497.255756823
     2265445.361      542509.903     2265589.052      542486.719
     2265685.265      542493.172     2265869.934      542590.536
     2265909.091      542737.173     2266025.615      542736.543
     2266091.909      542749.789     2266163.749      542784.919
     2266269.099      542800.8272266323.98079264542777.523351852
     2266336.441      542743.919     2266433.744      542748.678
     2266493.505      542738.6722266557.46356079542750.600008078
     2266627.666      542731.135     2266689.207      542739.162

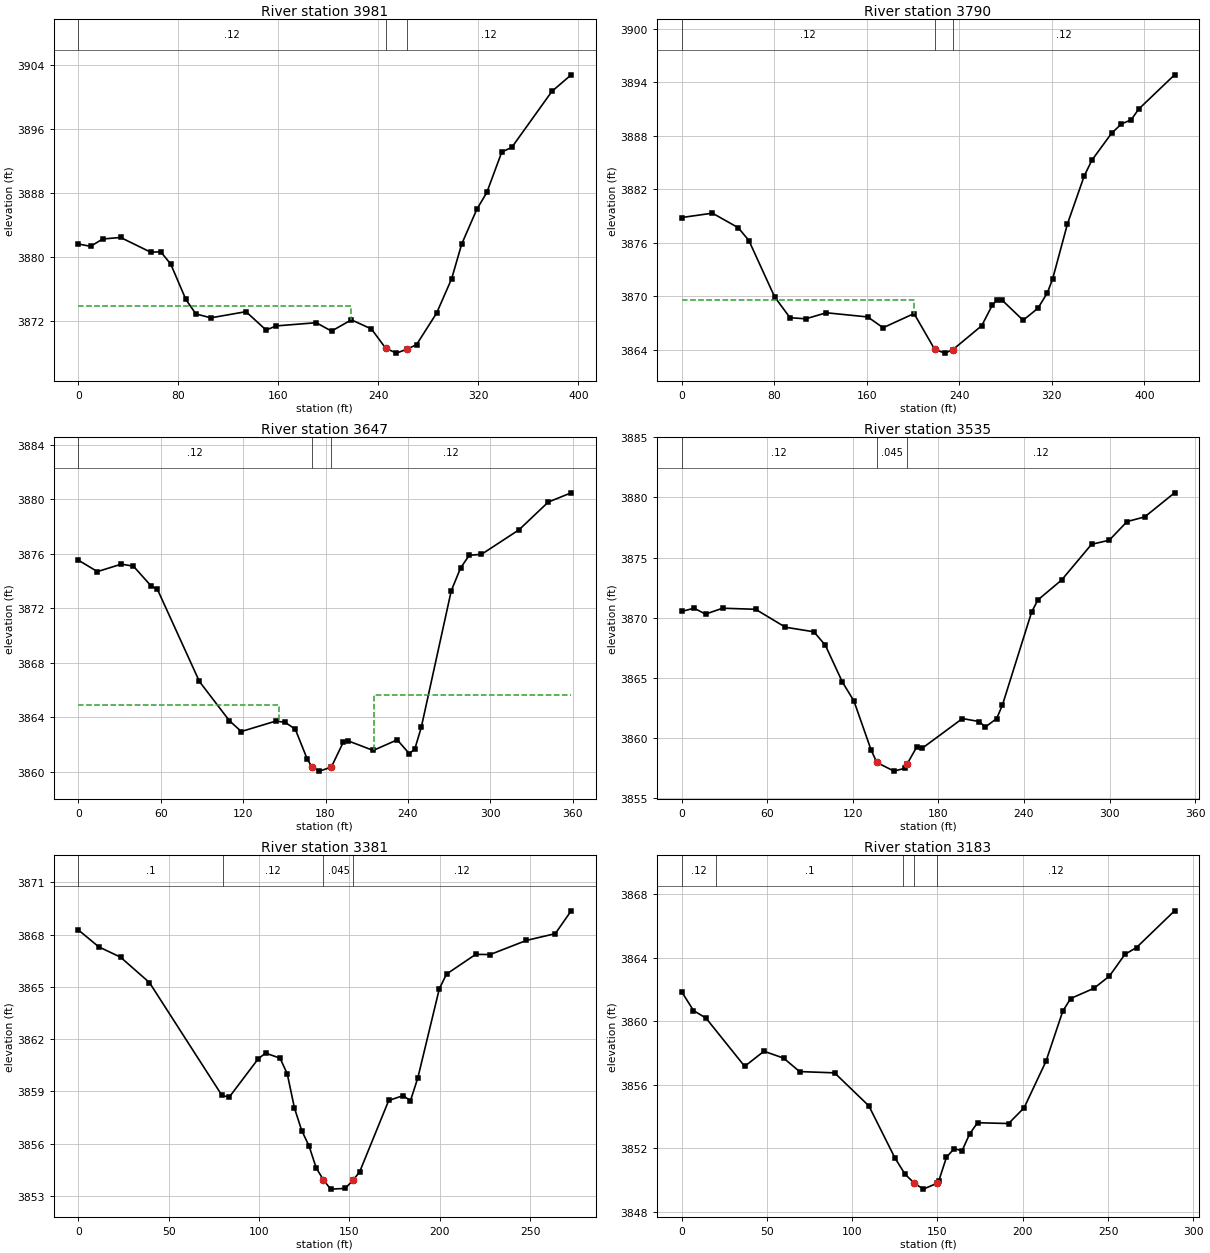
Type RM Length L Ch R = 1 ,3981    ,191.7,191.7,191.7
XS GIS Cut Line= 2
2263067.38802231543107.0126517852263037.48971471542713.849906831
#Sta/Elev= 30
       0 3881.68     9.9 3881.38    19.6  3882.3    33.9 3882.49      58 3880.65
      66  3880.7      74 3879.17    86.1 3874.75    94.1 3872.94   106.1 3872.45
   134.2 3873.22   150.3 3870.92   158.3 3871.44   190.4 3871.84   202.6 3870.79
   218.5  3872.2   234.5 3871.06     246 3868.64   254.5 3868.04   263.13868.542
   270.6  3869.1   286.7 3873.05   298.7 3877.34   306.7 3881.66   318.8    3886
   326.8 3888.11   338.8 3893.17   346.8 3893.75   378.9 3900.75   394.3 3902.81
#Mann= 3 ,-1,0
       0     .12       0     246    .045       0   263.1     .12       0
#XS Ineff= 2 , 0
          218.58  3873.9
Permanent Ineff=
       F       F
Bank Sta=246,263.1
XS Rating Curve= 0 ,0
Exp/Cntr(USF)=0,0
Exp/Cntr=0.3,0.1

Type RM Length L Ch R = 1 ,3790    ,143.2,142.6,141.7
XS GIS Cut Line= 3
2263130.17446827543101.032990265 2263263.2219371542836.432967995
2263219.86939108542713.849906831
#Sta/Elev= 30
       0 3878.84    26.7 3879.33      49  3877.7    58.2 3876.26    80.4 3869.95
    93.7  3867.6   107.3 3867.47   125.2 3868.15     161 3867.68   174.2 3866.47
     201 3868.06   218.9 3864.03   227.8 3863.62   234.63864.014   259.5  3866.7
   268.5 3868.97   272.9 3869.61   277.4 3869.53   295.3 3867.31   308.1 3868.66
   316.2 3870.38   320.8 3871.95   333.6 3878.12   348.1 3883.51   354.8 3885.29
   371.7 3888.29   380.2 3889.34   388.7 3889.81   395.1    3891   426.2 3894.86
#Mann= 3 ,-1,0
       0     .12       0   218.9    .045       0   234.6     .12       0
#XS Ineff= 2 , 0
          200.55 3869.63
Permanent Ineff=
       F       F
Bank Sta=218.9,234.6
XS Rating Curve= 0 ,0
Exp/Cntr(USF)=0,0
Exp/Cntr=0.3,0.1

Type RM Length L Ch R = 1 ,3647    ,118.1,112.4,107.3
XS GIS Cut Line= 2
2263294.61516008543110.0024825452263438.12703657542781.121098933
#Sta/Elev= 30
       0 3875.54      14 3874.69    31.4 3875.24    40.2 3875.09    53.3 3873.61
    57.6  3873.4    88.2 3866.62     110 3863.74   118.7 3862.94   143.9 3863.71
   150.7 3863.61     158 3863.11   166.7 3860.91   170.2 3860.32   175.5 3860.03
   184.2 3860.32   192.9 3862.15   196.3 3862.26   214.7 3861.55   232.2 3862.33
   240.9 3861.32   244.9 3861.63   249.7 3863.25   271.5 3873.28   278.3 3874.96
   284.6 3875.89   293.5 3875.96   320.8 3877.76   342.1  3879.8   358.8 3880.48
#Mann= 3 ,-1,0
       0     .12       0   170.2    .045       0   184.2     .12       0
#XS Ineff= 2 , 0
          146.01 3864.87  215.58         3865.63
Permanent Ineff=
       F       F
Bank Sta=170.2,184.2
XS Rating Curve= 0 ,0
Exp/Cntr(USF)=0,0
Exp/Cntr=0.3,0.1

Type RM Length L Ch R = 1 ,3535    ,155.9,153.8,152.7
XS GIS Cut Line= 3
2263469.52025955543121.9618055862263476.99483645542894.734667817
2263444.10669809542781.121098933
#Sta/Elev= 30
       0 3870.52     8.8 3870.79    16.8  3870.3    28.8 3870.79    51.9  3870.7
    72.8 3869.21    92.8 3868.83   100.8 3867.71   112.8 3864.64   120.8 3863.09
   132.9    3859   136.9 3857.97   148.9 3857.25   156.9  3857.5   158.3 3857.88
   164.9 3859.26   168.9 3859.17   196.9 3861.62   208.7 3861.37   212.9 3860.91
   220.9 3861.62   224.9 3862.73   245.4 3870.47   249.8 3871.48   266.4 3873.13
   287.4  3876.1   299.8 3876.44   312.3 3877.99   324.7 3878.38   345.6 3880.38
#Mann= 3 ,-1,0
       0     .12       0   136.9    .045       0   158.3     .12       0
Bank Sta=136.9,158.3
XS Rating Curve= 0 ,0
Exp/Cntr(USF)=0,0
Exp/Cntr=0.3,0.1

Type RM Length L Ch R = 1 ,3381    ,202.9,197.6,192.3
XS GIS Cut Line= 2
2263635.45586673543096.5482441252263619.01179755542824.473644955
#Sta/Elev= 30
       0 3868.28    11.4  3867.3    23.4 3866.71    39.4 3865.25    79.5 3858.77
    83.5 3858.67    99.6 3860.88   103.6  3861.2   111.6 3860.91   115.6 3860.01
   119.6 3858.04   123.6 3856.75   127.6 3855.88   131.6 3854.61   135.6 3853.92
   139.6 3853.39   147.6 3853.43   152.23853.922   155.7  3854.4   171.7 3858.48
   179.7 3858.76   183.7 3858.46   187.8 3859.78   199.7  3864.9   203.7 3865.74
   219.8 3866.87   227.8 3866.86   247.8 3867.67   263.8 3868.06   272.6 3869.37
#Mann= 4 ,-1,0
       0      .1       0      80     .12       0   135.6    .045       0
   152.2     .12       0
Bank Sta=135.6,152.2
XS Rating Curve= 0 ,0
Exp/Cntr(USF)=0,0
Exp/Cntr=0.3,0.1

Type RM Length L Ch R = 1 ,3183    ,200.2,201.1,201.8
XS GIS Cut Line= 2
 2263885.1067352543033.7617981622263747.57452024542779.626183553
#Sta/Elev= 30
       0 3861.86       7 3860.66    14.3 3860.19      37 3857.15    48.3  3858.1
    59.8 3857.67    69.2 3856.82    89.7 3856.74   109.8 3854.66   125.1 3851.38
     131 3850.36   136.4  3849.8   141.7 3849.42   149.6 3849.78   150.8 3849.94
   155.3 3851.43   159.8 3851.97   164.4 3851.83   168.9  3852.9   173.5  3853.6
   191.7 3853.55   200.8 3854.54   213.6 3857.46   223.5 3860.63   228.1 3861.42
   241.7 3862.06   250.8 3862.83   259.9  3864.2   266.7 3864.63     289 3866.94
#Mann= 5 ,-1,0
       0     .12       0      20      .1       0     130     .12       0
   136.4    .045       0   149.6     .12       0
Bank Sta=136.4,149.6
XS Rating Curve= 0 ,0
Exp/Cntr(USF)=0,0
Exp/Cntr=0.3,0.1

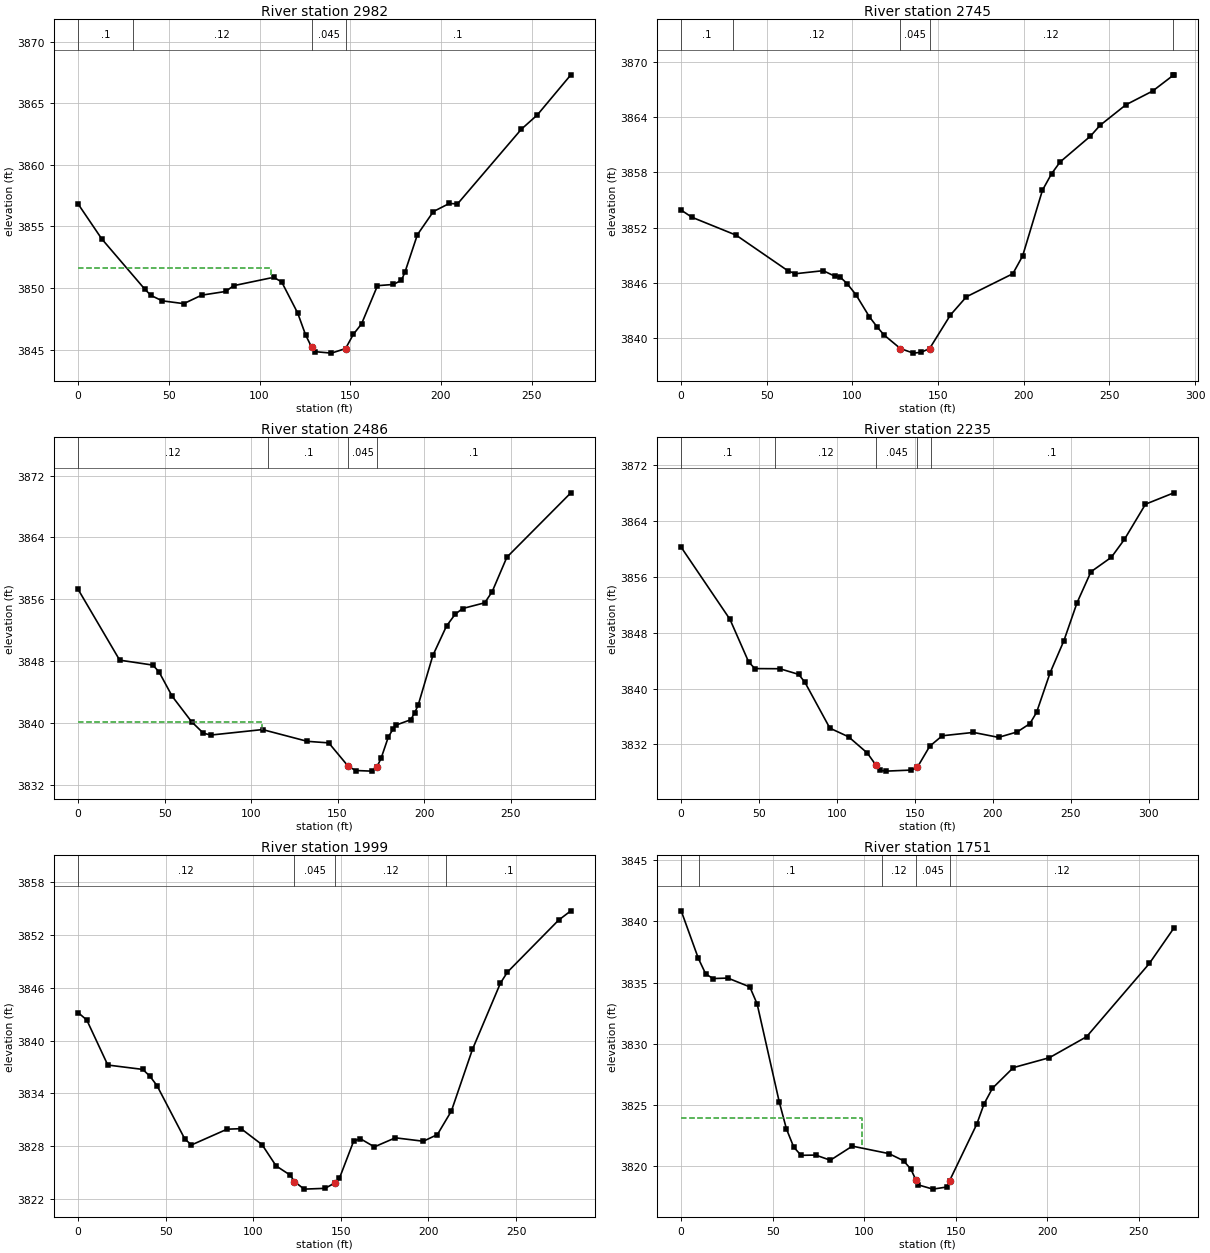
Type RM Length L Ch R = 1 ,2982    ,236.6,237.3,237.9
XS GIS Cut Line= 2
2264055.52708853542947.0567061192263941.91351964 542700.39566841
#Sta/Elev= 30
       0 3856.82      13 3853.99    36.7 3849.91    40.1  3849.4    46.3 3848.96
    58.2 3848.73    68.1 3849.42    81.3 3849.72    85.7 3850.19   107.8 3850.87
   112.2 3850.49     121 3847.97   125.4 3846.18   128.73845.185   130.6 3844.83
   139.6 3844.71   147.4 3845.08   151.7 3846.24   156.2 3847.08     165 3850.19
   173.8 3850.29   178.2 3850.63   180.1 3851.27     187 3854.33   195.8 3856.21
   204.6 3856.87   209.1 3856.83   244.3  3862.9   253.1 3864.06   271.6 3867.32
#Mann= 4 ,-1,0
       0      .1       0      30     .12       0   128.7    .045       0
   147.4      .1       0
#XS Ineff= 2 , 0
          106.23 3851.63
Permanent Ineff=
       F       F
Bank Sta=128.7,147.4
XS Rating Curve= 0 ,0
Exp/Cntr(USF)=0,0
Exp/Cntr=0.3,0.1

Type RM Length L Ch R = 1 ,2745    ,256.2,258.9,256.9
XS GIS Cut Line= 3
2264263.32032635542846.8973756562264193.05930349542673.487191569
2264119.80844987542604.721084087
#Sta/Elev= 30
       0 3853.92     6.2 3853.15    32.1  3851.2    62.3 3847.34    66.6 3847.02
    82.9 3847.35    89.7 3846.75    92.5 3846.71    96.8 3845.96     102 3844.75
   109.8 3842.37   114.3 3841.27   118.4 3840.38     128  3838.9   135.6 3838.41
     140  3838.5     145  3838.9   157.2 3842.55   166.5 3844.52   193.6 3847.02
   199.3 3848.94   210.9 3856.08   216.2 3857.86   221.2 3859.14   238.9 3861.94
   244.5 3863.11   259.6 3865.34   275.2 3866.83   287.1 3868.52   287.6 3868.59
#Mann= 5 ,-1,0
       0      .1       0      30     .12       0     128    .045       0
     145     .12       0   287.1      .1       0
Bank Sta=128,145
XS Rating Curve= 0 ,0
Exp/Cntr(USF)=0,0
Exp/Cntr=0.3,0.1

Type RM Length L Ch R = 1 ,2486    ,244.8,251.4,253.8
XS GIS Cut Line= 2
2264475.59831032542728.7990606312264373.94406448542462.704122982
#Sta/Elev= 30
       0 3857.28      24 3848.15    43.2 3847.51    46.7 3846.65    54.4 3843.47
    65.6 3840.19    72.4 3838.71    76.7 3838.47   106.6 3839.18   132.5 3837.66
   144.9 3837.46   156.1 3834.45   160.4 3833.89   169.7 3833.81   172.8 3834.37
   175.2 3835.49   179.4 3838.25   182.1 3839.24   183.7 3839.75   192.3 3840.45
   194.5 3841.31   196.6 3842.33   205.1 3848.76     213 3852.56     218 3854.08
   222.3 3854.82   235.1 3855.56   239.4    3857   247.9 3861.45   284.9 3869.77
#Mann= 4 ,-1,0
       0     .12       0     110      .1       0   156.1    .045       0
   172.8      .1       0
#XS Ineff= 2 , 0
          106.56 3840.18
Permanent Ineff=
       F       F
Bank Sta=156.1,172.8
XS Rating Curve= 0 ,0
Exp/Cntr(USF)=0,0
Exp/Cntr=0.3,0.1

Type RM Length L Ch R = 1 ,2235    ,237.3,236.2,237.1
XS GIS Cut Line= 3
2264668.44239435 542688.436345372264656.48307131542465.693953742
2264619.11018681542380.483777079
#Sta/Elev= 30
       0 3860.28    31.3 3849.94    43.3 3843.83    47.3 3842.88    63.3 3842.86
    75.4 3842.05    79.4 3840.91    95.4 3834.34   107.4  3833.1   119.4 3830.78
   125.13828.993   127.4 3828.28   131.4 3828.18   147.5 3828.33   151.6 3828.76
   159.5 3831.76   167.5 3833.25   187.5 3833.73   203.6 3833.02   215.6  3833.8
   223.7 3834.98     228 3836.59   236.7 3842.28   245.5 3846.85     254 3852.33
   262.9 3856.76     276 3858.84   284.4 3861.41   297.9 3866.45   316.1 3868.08
#Mann= 5 ,-1,0
       0      .1       0      60     .12       0   125.1    .045       0
   151.6     .12       0     160      .1       0
Bank Sta=125.1,151.6
XS Rating Curve= 0 ,0
Exp/Cntr(USF)=0,0
Exp/Cntr=0.3,0.1

Type RM Length L Ch R = 1 ,1999    ,246,247.1,247.8
XS GIS Cut Line= 2
2264898.65936288542642.0939685882264886.70003984542361.049877138
#Sta/Elev= 30
       0 3843.17     4.9 3842.34    16.9 3837.22    36.9 3836.72      41 3835.94
      45 3834.88    60.9 3828.81    64.7 3828.14      85 3829.93      93 3829.99
     105 3828.17     113 3825.76     121 3824.72   123.53823.976     129 3823.12
     141 3823.21   146.93823.863   149.2 3824.37   157.3 3828.58   161.1 3828.85
   169.1 3827.92   181.1 3828.95   197.1 3828.56   205.1 3829.32   213.1    3832
   225.1 3838.99   241.1 3846.53   245.1 3847.78   274.3 3853.68   281.3 3854.74
#Mann= 4 ,-1,0
       0     .12       0   123.5    .045       0   146.9     .12       0
     210      .1       0
Bank Sta=123.5,146.9
XS Rating Curve= 0 ,0
Exp/Cntr(USF)=0,0
Exp/Cntr=0.3,0.1

Type RM Length L Ch R = 1 ,1751    ,175.3,175.7,176.1
XS GIS Cut Line= 2
2265134.85599293542634.6193916882265142.33056983542365.534623278
#Sta/Elev= 30
       0 3840.87     9.4 3836.98    13.4 3835.72    17.4 3835.34    25.5 3835.38
    37.5 3834.66    41.5 3833.27    53.6 3825.26    57.5 3823.07    61.5 3821.58
    65.5 3820.91    73.5 3820.93    81.5 3820.51    93.5 3821.66   113.5 3821.05
   121.5 3820.47   125.5 3819.78  128.19 3818.92   129.5  3818.5   137.5 3818.15
   145.5 3818.33   146.7 3818.85   161.5 3823.45   165.5 3825.11   170.1 3826.39
   181.5 3828.07   201.2 3828.88   221.5 3830.59   255.8 3836.57   269.2 3839.46
#Mann= 5 ,-1,0
       0     .12       0      10      .1       0     110     .12       0
  128.19    .045       0   146.7     .12       0
#XS Ineff= 2 , 0
           99.02 3823.95
Permanent Ineff=
       F       F
Bank Sta=128.19,146.7
XS Rating Curve= 0 ,0
Exp/Cntr(USF)=0,0
Exp/Cntr=0.3,0.1

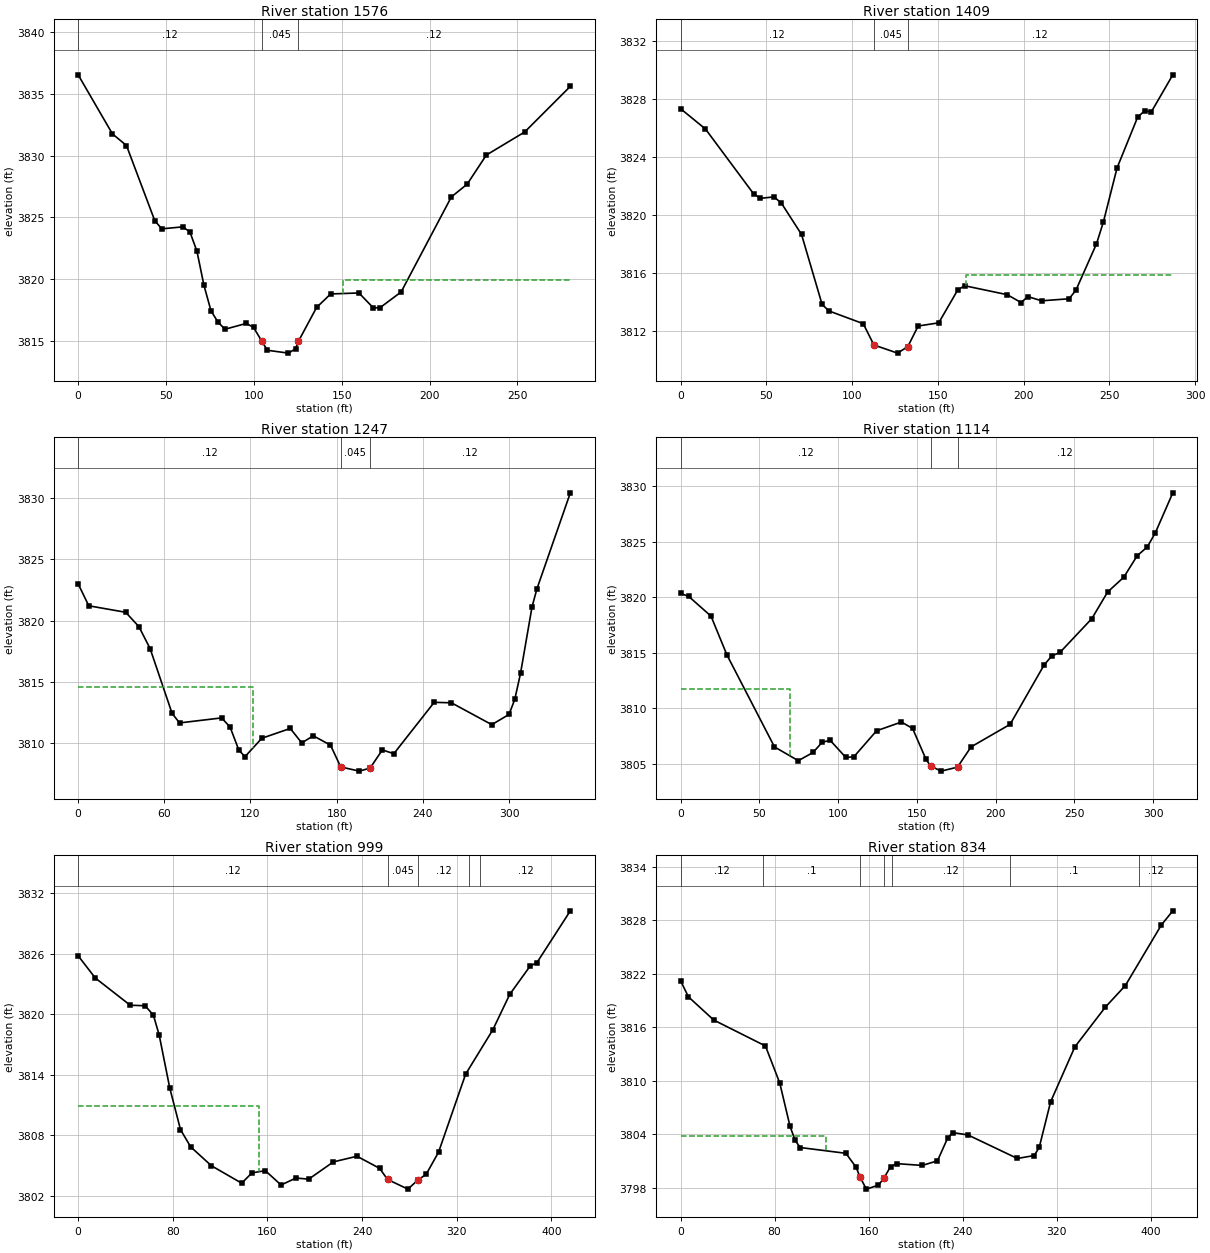
Type RM Length L Ch R = 1 ,1576    ,167.5,166.7,165.7
XS GIS Cut Line= 3
2265306.77126163542616.6804071272265317.23566929 542429.81598462
2265276.87295403542346.100723337
#Sta/Elev= 30
       0 3836.52    19.5 3831.75    27.5 3830.81    43.6 3824.74    47.6 3824.08
    59.6 3824.24    63.6 3823.83    67.6 3822.27    71.6 3819.51    75.6 3817.46
    79.6 3816.54    83.6 3815.97    95.7 3816.44    99.8 3816.12   104.5 3815.01
   107.7 3814.27   119.7 3814.04   123.7 3814.39   125.3 3814.98   135.7 3817.73
   143.7 3818.82   159.8  3818.9   167.8 3817.72   171.6 3817.69   183.8 3818.98
   212.4 3826.66   221.4 3827.69   232.3 3830.04   254.1  3831.9   280.1 3835.59
#Mann= 3 ,-1,0
       0     .12       0   104.5    .045       0   125.3     .12       0
#XS Ineff= 2 , 0
                          150.82         3819.91
Permanent Ineff=
       F       F
Bank Sta=104.5,125.3
XS Rating Curve= 0 ,0
Exp/Cntr(USF)=0,0
Exp/Cntr=0.3,0.1

Type RM Length L Ch R = 1 ,1409    ,160.9,162.2,163.2
XS GIS Cut Line= 2
2265480.18144572542631.6295609282265478.68653034542344.605807957
#Sta/Elev= 30
       0  3827.3    14.5  3825.9    42.5 3821.44    46.5 3821.12    54.5 3821.22
    58.8 3820.78    70.5 3818.63    82.5  3813.8    86.5 3813.35   106.5 3812.47
   112.73811.003   126.5 3810.44   132.53810.893   138.5 3812.31   150.5 3812.53
   161.6  3814.8   165.6 3815.09   190.5 3814.47   198.5 3813.93   202.5 3814.34
   210.5 3814.05   226.5 3814.19   230.5 3814.78   242.5 3817.98   246.5 3819.48
   254.5 3823.22   266.5 3826.72   270.5 3827.15   274.5 3827.09     287 3829.64
#Mann= 3 ,-1,0
       0     .12       0   112.7    .045       0   132.5     .12       0
#XS Ineff= 2 , 0
                          166.56         3815.83
Permanent Ineff=
       F       F
Bank Sta=112.7,132.5
XS Rating Curve= 0 ,0
Exp/Cntr(USF)=0,0
Exp/Cntr=0.3,0.1

Type RM Length L Ch R = 1 ,1247    ,125.5,133.4,142.3
XS GIS Cut Line= 3
 2265564.5057466542661.8785276922265635.58640898542538.034589475
2265649.10688367542338.626146437
#Sta/Elev= 30
       0 3822.99     7.4  3821.2    33.1 3820.67    42.3  3819.5    50.1 3817.71
    65.4 3812.43    70.6 3811.65    99.9 3812.06   105.8 3811.31   111.8 3809.46
   116.1 3808.89   127.9  3810.4   147.7  3811.2   155.7 3810.02   163.7  3810.6
   175.7 3809.84  182.82 3808.06   195.8 3807.72   203.3 3807.97   211.8 3809.45
   219.8 3809.14   247.9 3813.33   259.9 3813.29     288 3811.51     300 3812.34
     304 3813.57     308 3815.68     316  3821.1   319.4 3822.57   342.7 3830.41
#Mann= 3 ,-1,0
       0     .12       0  182.82    .045       0   203.3     .12       0
#XS Ineff= 2 , 0
          121.58 3814.55
Permanent Ineff=
       F       F
Bank Sta=182.82,203.3
XS Rating Curve= 0 ,0
Exp/Cntr(USF)=0,0
Exp/Cntr=0.3,0.1

Type RM Length L Ch R = 1 ,1114    ,114.7,114.7,115.4
XS GIS Cut Line= 2
2265661.06620671542664.5176992892265850.92045997  542416.3617462
#Sta/Elev= 30
       0 3820.35     5.1 3820.09    19.3 3818.31    29.4 3814.82    59.6 3806.54
    74.7  3805.3    84.1 3806.04    89.8 3806.95    94.9 3807.14   104.9 3805.59
     110 3805.65   124.4 3807.99   140.2 3808.78   147.3  3808.2   155.8 3805.42
   158.7 3804.82   165.4 3804.36   175.8 3804.72   184.4 3806.54   209.2 3808.57
   230.8 3813.92   235.7 3814.73   240.9 3815.05   261.1 3818.09   271.1 3820.48
   281.4 3821.82   289.9 3823.75   296.3 3824.54   301.4 3825.81   312.5 3829.41
#Mann= 3 ,-1,0
       0     .12       0   158.7    .045       0   175.8     .12       0
#XS Ineff= 2 , 0
           69.26 3811.74
Permanent Ineff=
       F       F
Bank Sta=158.7,175.8
XS Rating Curve= 0 ,0
Exp/Cntr(USF)=0,0
Exp/Cntr=0.3,0.1

Type RM Length L Ch R = 1 ,999     ,167.9,164.8,165.1
XS GIS Cut Line= 2
2265707.40858349542805.0397450142265948.08995968542465.693953742
#Sta/Elev= 30
       0 3825.78    14.5 3823.58      44 3820.88    56.6 3820.83    63.6  3819.9
    68.5 3817.92    77.4 3812.69    86.5 3808.55    95.1 3806.84   112.6 3804.97
   138.2 3803.24   146.9 3804.26   158.2 3804.48   171.5 3803.06   184.1 3803.75
   194.9 3803.64   215.7 3805.35   235.7 3805.91   254.8 3804.71   261.5 3803.61
   278.7 3802.65   287.4 3803.58   294.1 3804.11   304.6 3806.31   327.5 3814.05
   350.5 3818.45   364.8 3821.96     382 3824.76   387.8 3825.11     416 3830.24
#Mann= 5 ,-1,0
       0     .12       0   261.5    .045       0   287.4     .12       0
     330      .1       0     340     .12       0
#XS Ineff= 2 , 0
          152.63 3810.86
Permanent Ineff=
       F       F
Bank Sta=261.5,287.4
XS Rating Curve= 0 ,0
Exp/Cntr(USF)=0,0
Exp/Cntr=0.3,0.1

Type RM Length L Ch R = 1 ,834     ,128.4,125.1,120.5
XS GIS Cut Line= 2
2265847.93062921542887.2600909172266007.88657488542500.077007483
#Sta/Elev= 30
       0 3821.22     6.6 3819.42    28.2 3816.81    72.2  3813.9    84.4 3809.73
    93.1 3804.89    97.5 3803.29   101.8  3802.5   140.7 3801.85   149.4 3800.27
   152.8 3799.15   158.1 3797.83   168.3 3798.27     173 3799.05   178.7 3800.37
     184 3800.69   205.7 3800.49   218.6 3801.01   227.3 3803.57   231.6 3804.18
   244.6 3803.91   286.6 3801.27   300.9  3801.6   305.2 3802.51   314.9 3807.63
   335.5 3813.79   361.5 3818.26   378.5 3820.68   409.2 3827.49   418.9 3829.07
#Mann= 7 ,-1,0
       0     .12       0      70      .1       0   152.8    .045       0
     173      .1       0     180     .12       0     280      .1       0
     390     .12       0
#XS Ineff= 2 , 0
          124.04 3803.75
Permanent Ineff=
       F       F
Bank Sta=152.8,173
XS Rating Curve= 0 ,0
Exp/Cntr(USF)=0,0
Exp/Cntr=0.3,0.1

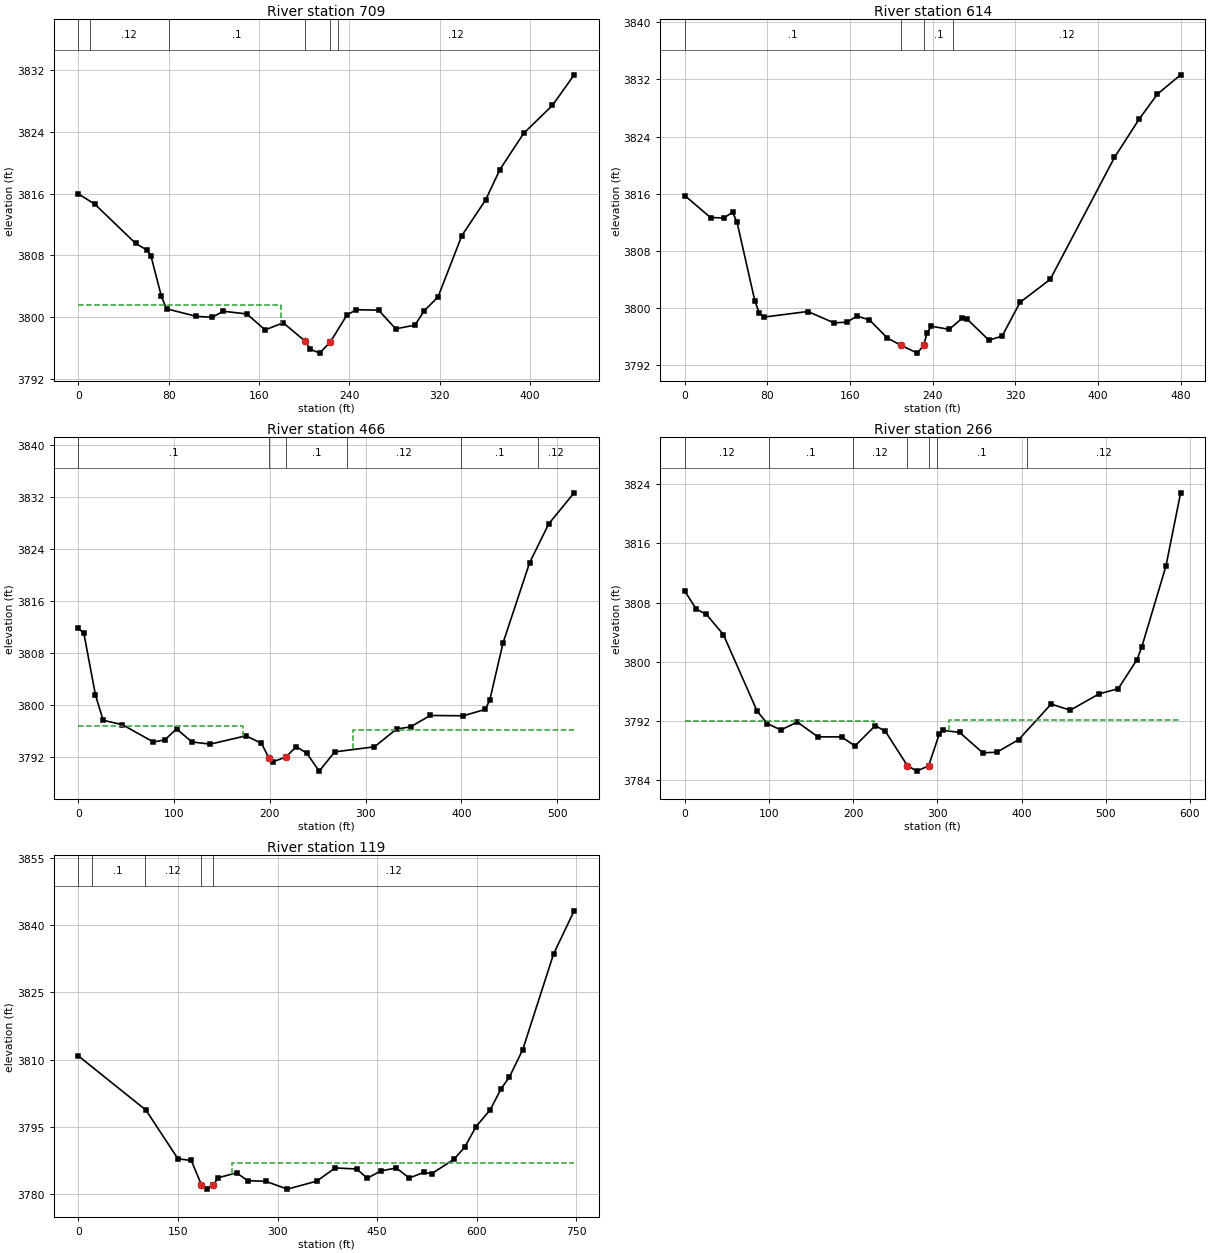
Type RM Length L Ch R = 1 ,709     ,90.3,94.8,98.4
XS GIS Cut Line= 4
2265959.75977635542934.1180911932266025.38020455542810.054469116
2266044.86126918542637.8008450772266084.84871761542518.863818954
#Sta/Elev= 30
       0 3815.98    14.6 3814.64    50.8 3809.55    60.8 3808.69    64.4 3807.89
    73.5 3802.73    78.1 3801.08   104.6 3800.09   118.7 3799.98   128.3 3800.76
   149.3 3800.41   165.4 3798.34   181.5 3799.26   200.8 3796.89   205.6 3795.83
   213.7 3795.33   223.2 3796.77   237.7 3800.22   245.9 3800.96     266  3800.9
   281.1 3798.48   298.2 3798.96   306.4 3800.82   318.6 3802.61   339.7 3810.56
   360.8  3815.2   373.4 3819.12   394.5 3823.83   419.9 3827.44   439.2 3831.41
#Mann= 6 ,-1,0
       0      .1       0      10     .12       0      80      .1       0
   200.8    .045       0   223.2      .1       0  230.35     .12       0
#XS Ineff= 2 , 0
          179.78 3801.51
Permanent Ineff=
       F       F
Bank Sta=200.8,223.2
XS Rating Curve= 0 ,0
Exp/Cntr(USF)=0,0
Exp/Cntr=0.3,0.1

Type RM Length L Ch R = 1 ,614     ,152.7,148.6,145.2
XS GIS Cut Line= 3
2266045.25945938 542972.47026758 2266163.3577744542660.032953149
2266124.48997452542519.510907424
#Sta/Elev= 30
       0 3815.74    24.9 3812.68    37.7 3812.62    46.3 3813.41    50.6 3811.99
    67.7 3801.07    71.9 3799.38    76.2 3798.75     119 3799.54   144.6 3797.94
   156.9 3798.06   166.6 3798.89   178.6 3798.38   195.9 3795.85   208.8 3794.84
   225.1 3793.72   231.4  3794.9   234.4 3796.56   238.7 3797.48   255.8 3797.04
   268.6 3798.62   272.9 3798.51   294.3 3795.53   307.1 3796.11   324.4 3800.82
   353.6 3804.03   415.8 3821.08   439.7 3826.44   457.3 3829.93   479.8 3832.63
#Mann= 4 ,-1,0
       0      .1       0   208.8    .045       0   231.4      .1       0
     260     .12       0
Bank Sta=208.8,231.4
XS Rating Curve= 0 ,0
Exp/Cntr(USF)=0,0
Exp/Cntr=0.3,0.1

Type RM Length L Ch R = 1 ,466     ,197.1,199.4,194.4
XS GIS Cut Line= 3
 2266240.6972346543006.9157537332266276.58340628542709.573188427
2266166.87425287542520.914457336
#Sta/Elev= 30
       0 3811.77     5.8 3810.95    17.9 3801.47    25.9 3797.59    46.1 3796.91
    78.3 3794.25    90.4 3794.58   102.5 3796.27   118.6 3794.26   137.7 3793.92
     175  3795.2   191.1 3794.06   198.8 3791.86   203.2 3791.21   216.93791.953
   227.4 3793.53   238.4 3792.55   251.5 3789.77   267.7 3792.73   309.2 3793.51
   332.3 3796.25   346.9 3796.58   367.4 3798.33   401.8 3798.28   424.9 3799.26
   429.5 3800.65   443.5 3809.52   471.2 3821.83   491.3 3827.83   517.7 3832.57
#Mann= 6 ,-1,0
       0      .1       0   198.8    .045       0   216.9      .1       0
     280     .12       0   399.5      .1       0   479.5     .12       0
#XS Ineff= 2 , 0
           171.8 3796.65  287.21          3796.1
Permanent Ineff=
       F       F
Bank Sta=198.8,216.9
XS Rating Curve= 0 ,0
Exp/Cntr(USF)=0,0
Exp/Cntr=0.3,0.1

Type RM Length L Ch R = 1 ,266     ,147.5,147.5,147.5
XS GIS Cut Line= 3
2266449.70891798543022.8277943132266421.87765387542647.776287543
2266271.64993669542496.914923099
#Sta/Elev= 30
       0 3809.55    13.7 3807.11    25.7  3806.4    45.8 3803.69    85.9 3793.35
    97.9 3791.67     114  3790.8   133.7 3791.87   158.1 3789.87   186.2 3789.86
   202.2 3788.64   226.3 3791.39   238.3 3790.61   264.3    3786   275.5 3785.24
  289.61 3785.96   302.5 3790.31   306.5 3790.75   326.5 3790.47     354 3787.71
   370.7 3787.79   396.7  3789.5   435.2  3794.3   457.9 3793.47   491.9 3795.66
   514.9 3796.38   537.2  3800.3   542.9 3802.03   571.5 3812.91     589 3822.83
#Mann= 7 ,-1,0
       0     .12       0     100      .1       0     200     .12       0
   264.3    .045       0  289.61     .12       0     300      .1       0
  406.08     .12       0
#XS Ineff= 2 , 0
          224.92 3792.04   314.1         3792.16
Permanent Ineff=
       F       F
Bank Sta=264.3,289.61
XS Rating Curve= 0 ,0
Exp/Cntr(USF)=0,0
Exp/Cntr=0.3,0.1

Type RM Length L Ch R = 1 ,119     ,,,
XS GIS Cut Line= 3
2266592.39848848542942.5719599792266547.55102708542465.693953742
2266290.42558171542390.948184739
#Sta/Elev= 30
       0 3810.82   101.8 3798.71   150.1 3787.82   170.1 3787.46  185.43 3782.01
   194.2 3781.08   203.5 3781.96   210.3 3783.58   238.4 3784.69   254.9 3782.95
   282.6 3782.78   314.8 3781.05     359 3782.83   386.9 3785.78   419.2 3785.55
   435.3 3783.48   455.4 3785.11     479 3785.78   498.3 3783.53     520 3784.77
   532.5 3784.52   565.8 3787.72   582.2 3790.48   599.1 3795.04     620  3798.7
     637 3803.53   649.1 3806.06   669.3 3812.19   715.8  3833.6   746.8 3843.23
#Mann= 5 ,-1,0
       0     .12       0      20      .1       0     100     .12       0
  185.43    .045       0   203.5     .12       0
#XS Ineff= 2 , 0
                          231.69          3786.9
Permanent Ineff=
       F       F
Bank Sta=185.43,203.5
XS Rating Curve= 0 ,0
Exp/Cntr(USF)=0,0
Exp/Cntr=0.3,0.1
LCMann Table=0

Chan Stop Cuts=-1
Use User Specified Reach Order=0
Composite Channel Slope=5